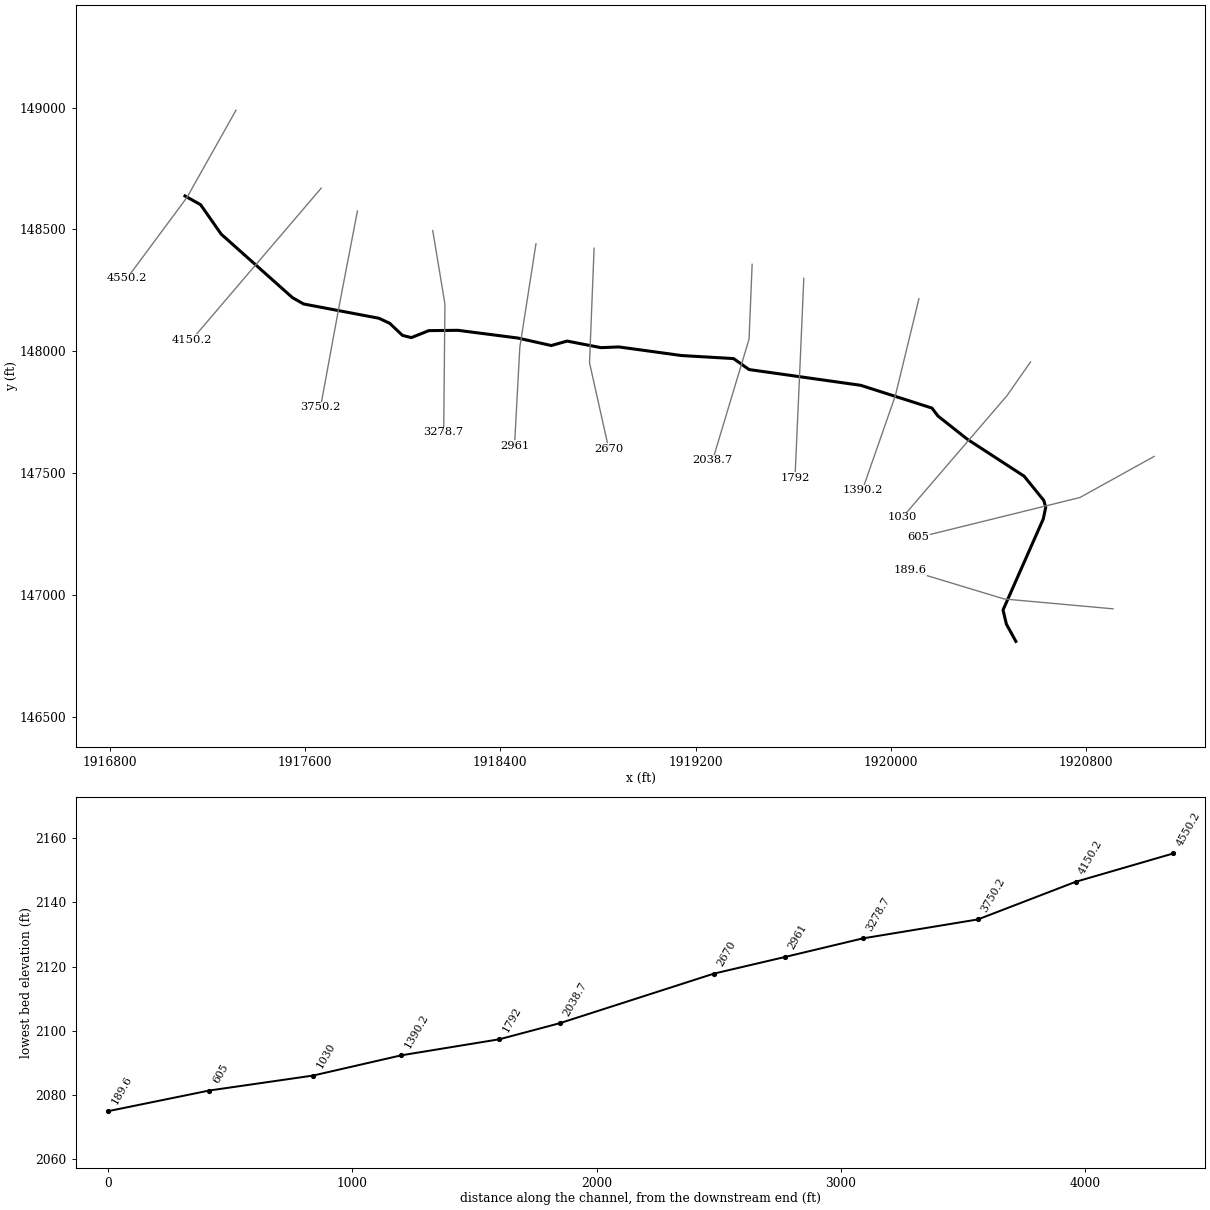
--- LshmtBrnch.prj (project) ---

Proj Title=LshmtBrnch
Current Plan=p01
Default Exp/Contr=0,0
English Units
Geom File=g01
Flow File=f01
Plan File=p01
BEGIN DESCRIPTION:
END DESCRIPTION:
DSS Export Rating Curves= 0
DSS Export Rating Curve Sorted= 0
DSS Export Volume Flow Curves= 0
DXF OffsetX= 0
DXF OffsetY= 0
DXF ScaleX= 0
DXF ScaleY= 0

--- LshmtBrnch.p01 (plan) ---

Plan Title=Floodplain
Program Version=4.00
Geom File=g01
Flow File=f01
K Sum by GR=0
Std Step Tol=0.01
Critical Tol=0.01
Num of Std Step Trials=20
Max Error Tol=0.3
Flow Tol Ratio=0.001
Split Flow NTrial=30
Split Flow Tol=0.02
Split Flow Ratio=0.02
Log Output Level=0
Friction Slope Method=1
Unsteady Friction Slope Method=2
Unsteady Bridges Friction Slope Method=1
Global Log Level=0
CheckData=False
Run HTab=0
Run UNet=0
Run PostProcess=0
UNET Theta=0
UNET Theta Warmup=0
UNET ZTol=0
UNET ZSATol=0
UNET MxIter=0
UNET MaxInSteps=0
UNET DtIC=0
UNET DtMin=0
UNET MaxCRTS=0
UNET WFStab=0
UNET SFStab=0
UNET WFX=0
UNET SFX=0
UNET DSS MLevel=0
UNET DZMax Abort=0
UNET Convert EG Bridges=0
UNET Use Existing IB Tables=0
UNET Froude Limit=0
UNET Froude Power=0
Write IC File=0
Echo Input=False
Echo Output=False
Write Detailed=0

--- LshmtBrnch.f01 (steady flow) ---

Flow Title=NFF Regression Equation
Program Version=4.00
Number of Profiles=1
Profile Names=P100yr
River Rch & RM=LshmtBrnch,Main      ,4550.2
566.1804
River Rch & RM=LshmtBrnch,Main      ,3750.2
584.3071
River Rch & RM=LshmtBrnch,Main      ,2038.7
631.9794
River Rch & RM=LshmtBrnch,Main      ,189.6
682.6304
Boundary for River Rch & Prof#=LshmtBrnch,Main      ,1
Up Type=0
Dn Type=3
Dn Slope=0.014375

--- LshmtBrnch.g01 (geometry) ---

Geom Title=USGS 3m DEM
Program Version=4.10

River Reach=LshmtBrnch      ,Main
Reach XY= 30
     1917109.052      148637.272     1917172.802       148601.53
     1917257.437      148480.436     1917549.104      148220.019
     1917594.676      148193.978      1917903.27      148135.383
     1917947.541       148114.55     1917999.624      148065.071
     1918036.083      148055.956     1918107.697      148084.602
     1918226.187      148085.905     1918472.152      148054.201
        1918609.      148023.404     1918674.104      148041.634
     1918812.714      148014.757     1918885.829      148017.643
     1919142.365      147982.356     1919355.506      147969.861
      1919418.99      147924.845     1919876.075      147860.206
     1920168.101      147766.712      1920192.34      147734.393
     1920312.972      147638.757     1920545.193      147487.419
     1920626.085      147387.669     1920634.014      147359.665
     1920623.917      147311.642     1920459.088      146937.803
     1920472.966       146879.76     1920511.785      146808.952

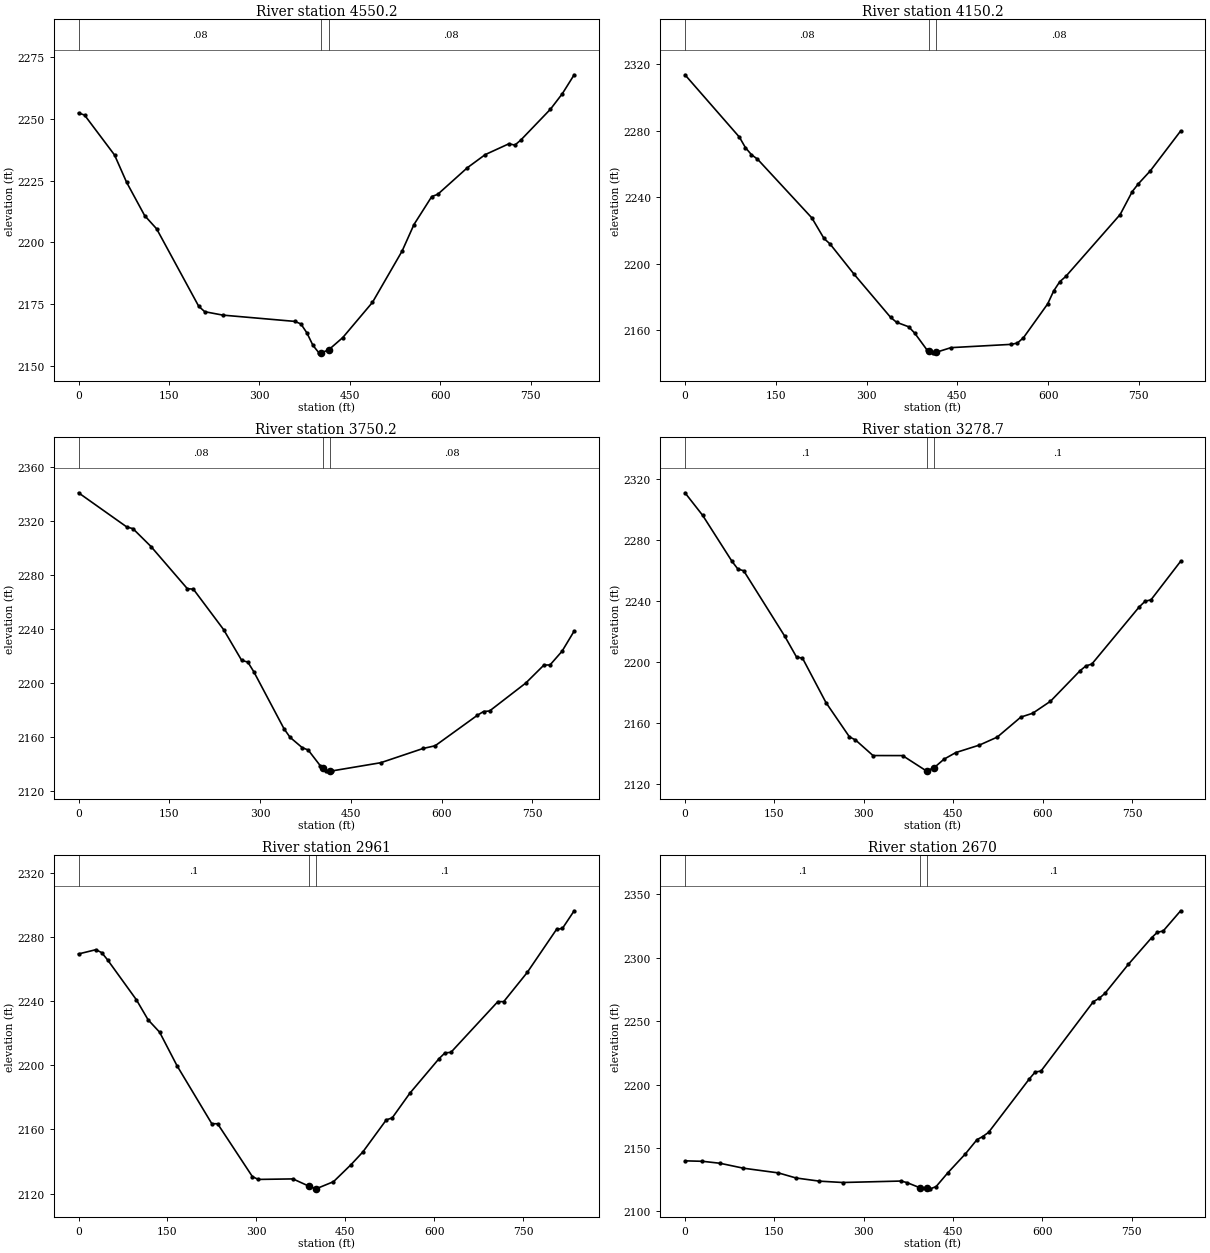
Type RM Length L Ch R = 1 ,4550.2  ,404.3,400,398.4
XS GIS Cut Line= 3
     1917317.704      148988.964     1917117.775      148632.381
     1916872.074      148299.878
#Sta/Elev= 30
       0 2252.44      10 2251.61    59.8 2235.42    79.8 2224.36   109.7 2210.89
   129.6 2205.52   199.4 2174.16   209.4 2171.96   239.3 2170.58     359 2168.03
   368.9    2167   378.9 2163.36   388.9 2158.32   398.8  2155.3   402.8 2155.32
   414.8 2156.48   438.3 2161.47   487.6 2175.74   536.8 2196.53   556.5 2207.28
     586 2218.61   595.8 2219.48     645 2230.27   674.6 2235.58     714 2239.98
   723.8 2239.43   733.6 2241.46   782.9 2253.99   802.6 2260.27   822.2 2267.92
#Mann= 3 , 0 , 0
       0     .08       0   402.8    .045       0   414.8     .08       0
Bank Sta=402.8,414.8
XS Rating Curve= 0 ,0
Exp/Cntr=0.3,0.1

Type RM Length L Ch R = 1 ,4150.2  ,389.1,400,411.1
XS GIS Cut Line= 3
     1917666.843      148669.426     1917401.296      148357.696
     1917135.749      148045.967
#Sta/Elev= 30
       0 2313.48    89.9 2276.04    99.9 2269.71   109.9 2265.46   119.8 2262.82
   209.7 2227.48   229.7 2215.16   239.7 2211.85   279.7 2193.55   339.6 2167.84
   349.6 2164.81   369.6 2162.11   379.5 2158.33   399.5  2148.4   403.5 2147.62
   409.5 2146.45   415.5 2146.83   439.5 2149.57   539.3 2151.55   549.3 2152.33
   559.3 2155.54   599.3 2175.85   609.3 2183.67   619.2 2189.15   629.2 2192.34
   719.1 2229.55   739.1 2243.34   749.1 2247.97   769.1 2255.86     819 2279.72
#Mann= 3 , 0 , 0
       0     .08       0   403.5    .045       0   415.5     .08       0
Bank Sta=403.5,415.5
XS Rating Curve= 0 ,0
Exp/Cntr=0.3,0.1

Type RM Length L Ch R = 1 ,3750.2  ,467.4,471.3,475
XS GIS Cut Line= 3
     1917815.144      148575.559     1917738.016       148173.39
     1917664.112      147770.598
#Sta/Elev= 30
       0 2340.74    79.9 2315.37    89.9 2314.17   119.8 2300.91   179.8  2269.7
   189.8 2269.31   239.7  2239.4   269.7  2216.5   279.7 2215.33   289.6 2208.18
   339.6 2165.87   349.6 2159.54   369.6 2151.92   379.5 2150.16   399.5  2138.5
   403.5 2137.06   409.5  2134.9   415.5 2134.79   419.5 2134.72   499.4 2140.74
   569.3 2151.28   589.3  2153.3   659.2 2175.93   669.2 2178.67   679.2 2179.07
   739.1 2199.79   769.1 2213.12   779.1 2213.16     799 2223.36     819 2238.29
#Mann= 3 , 0 , 0
       0     .08       0   403.5    .045       0   415.5     .08       0
Bank Sta=403.5,415.5
XS Rating Curve= 0 ,0
Exp/Cntr=0.3,0.1

Type RM Length L Ch R = 1 ,3278.7  ,320.6,317.6,314.6
XS GIS Cut Line= 3
     1918123.625      148495.149     1918173.549      148193.786
     1918168.441      147667.925
#Sta/Elev= 30
       0 2310.84    29.6 2296.09    78.8 2265.99    88.7 2260.93    98.5 2259.79
   167.5 2216.84   187.2 2203.24   197.1  2202.6   236.5 2173.48   275.9 2151.01
   285.8 2149.08   315.4 2138.81     365 2138.78   404.7  2128.8   405.7  2128.9
   417.7 2130.79   434.5 2136.43   454.3 2140.76     494 2145.68   523.8 2150.88
   563.4 2163.99   583.3 2166.51   613.1 2174.36   662.7 2194.34   672.6 2197.49
   682.5 2198.73   761.9  2236.1   771.8 2239.82   781.7 2240.77   831.4 2265.99
#Mann= 3 , 0 , 0
       0      .1       0   405.7    .045       0   417.7      .1       0
Bank Sta=405.7,417.7
XS Rating Curve= 0 ,0
Exp/Cntr=0.3,0.1

Type RM Length L Ch R = 1 ,2961    ,288.8,291,293.2
XS GIS Cut Line= 3
     1918546.334      148441.003     1918480.166      148016.123
     1918458.454      147610.822
#Sta/Elev= 30
       0 2269.39    29.3 2272.04    39.1 2270.21    48.9 2265.76    97.7 2240.78
   117.3 2228.39   136.8 2220.63   166.1 2199.75   224.8 2163.61   234.6 2163.57
   293.2 2130.66     303 2128.89   361.6 2129.21   388.5  2124.7   400.5 2123.02
     430 2127.47   459.7 2138.13   479.5    2146   519.1 2166.02     529 2167.22
   558.7 2182.56   608.2 2204.22   618.1 2207.75     628 2208.06   707.2 2239.69
   717.1 2239.67   756.7 2257.84   806.2 2284.73   816.1 2285.29   835.9 2296.29
#Mann= 3 , 0 , 0
       0      .1       0   388.5    .045       0   400.5      .1       0
Bank Sta=388.5,400.5
XS Rating Curve= 0 ,0
Exp/Cntr=0.3,0.1

Type RM Length L Ch R = 1 ,2670    ,636.2,630.8,625.5
XS GIS Cut Line= 3
     1918784.403      148422.721     1918765.682      147952.547
     1918844.261       147599.83
#Sta/Elev= 30
       0 2139.91    29.4 2139.55    58.8    2138      98 2134.11   156.8  2130.4
   186.3  2126.4   225.5  2123.9   264.7 2122.83   362.7 2123.98   372.5 2122.77
     394 2118.75     406 2118.23   411.7 2117.83   421.5 2119.61   441.1 2130.45
   470.6 2145.39   490.1 2156.62   499.8  2159.1   509.6  2162.4     578 2204.57
   587.8 2209.97   597.5 2210.72   685.4 2265.45   695.2 2268.11     705 2272.08
     744 2294.82   783.1 2315.84   792.8 2320.19   802.6 2321.19   831.9 2337.15
#Mann= 3 , 0 , 0
       0      .1       0     394    .045       0     406      .1       0
Bank Sta=394,406
XS Rating Curve= 0 ,0
Exp/Cntr=0.3,0.1

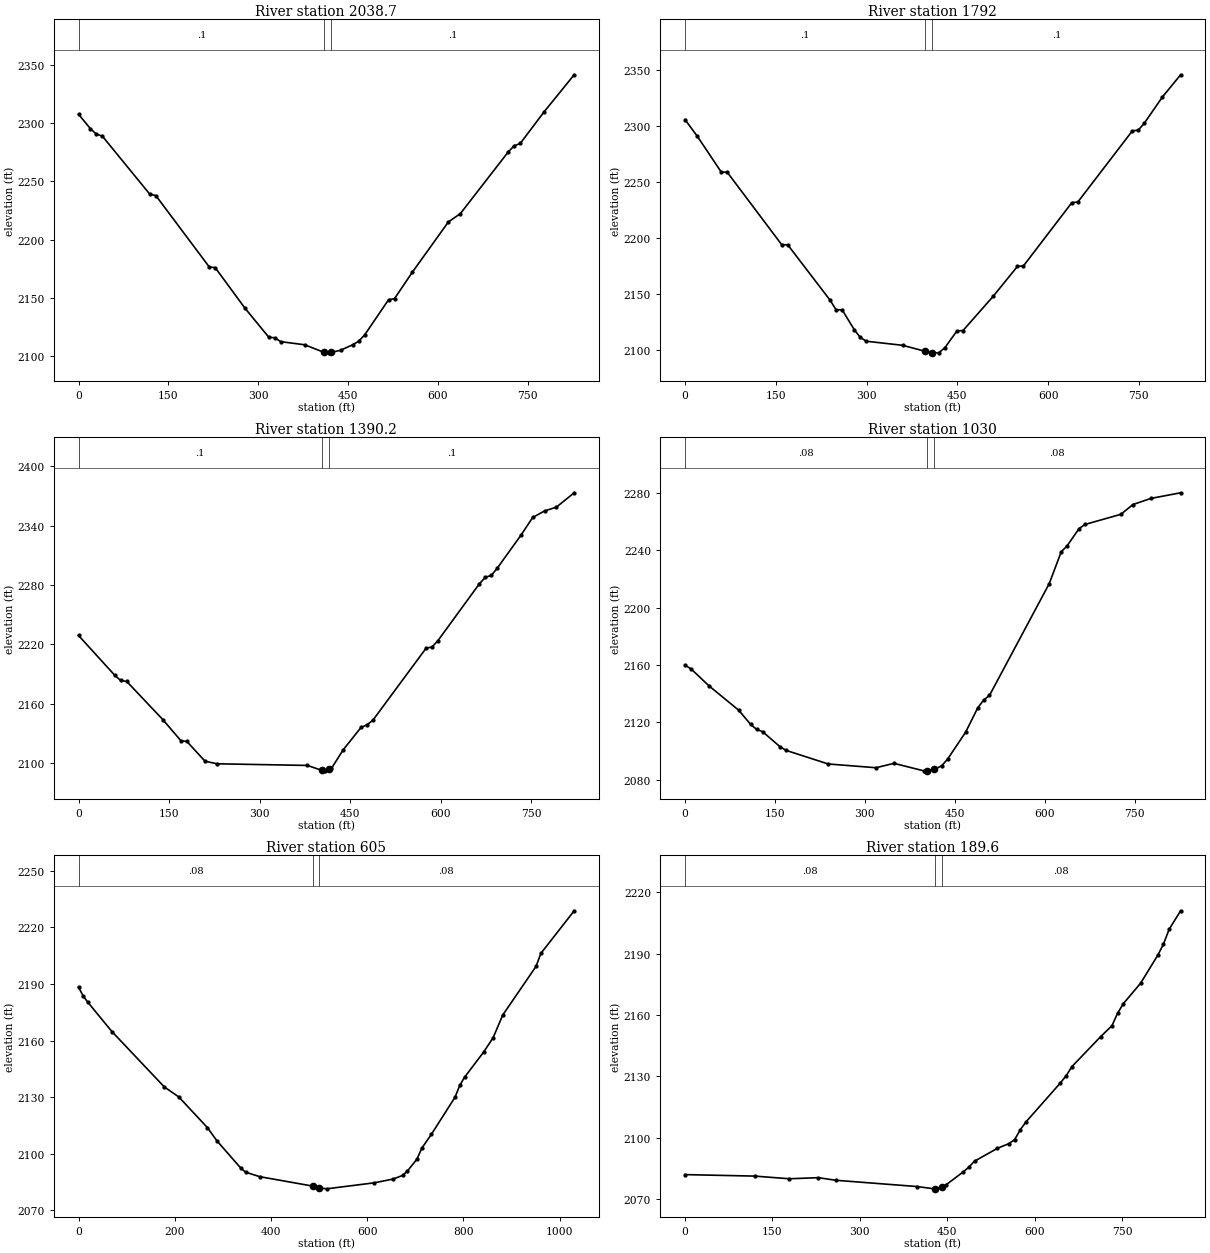
Type RM Length L Ch R = 1 ,2038.7  ,242,247.1,252.2
XS GIS Cut Line= 3
     1919431.647      148356.743      1919418.99      148049.504
     1919269.551      147551.795
#Sta/Elev= 30
       0 2307.93    19.8 2295.54    29.8 2290.74    39.7 2289.11     119 2239.01
     129 2237.88   218.2 2176.35   228.1 2175.79   277.7  2140.9   317.5 2115.86
   327.5 2115.31   337.5    2112   377.4 2109.32   410.2  2102.7   417.4 2102.37
   422.2 2102.73   437.4 2104.61   457.4 2109.29   467.4  2112.3   477.4  2117.7
   517.4 2148.07   527.4 2149.08   557.3 2171.95   617.3 2215.16   637.3  2222.3
   717.2 2275.47   727.2 2280.74   737.2 2282.73   777.2 2310.12   827.2 2341.91
#Mann= 3 , 0 , 0
       0      .1       0   410.2    .045       0   422.2      .1       0
Bank Sta=410.2,422.2
XS Rating Curve= 0 ,0
Exp/Cntr=0.3,0.1

Type RM Length L Ch R = 1 ,1792    ,405.9,401.8,395.7
XS GIS Cut Line= 3
     1919643.218      148298.991     1919625.429      147889.878
     1919607.103      147480.787
#Sta/Elev= 30
       0 2305.93      20 2291.29    59.9    2259    69.9 2258.77   159.8 2194.06
   169.8 2193.94   239.7 2144.48   249.7 2135.82   259.7 2135.82   279.7 2118.09
   289.6 2111.16   299.6 2107.75   359.6 2104.09   396.8 2098.74   408.8 2097.43
   409.5 2097.36   419.5 2097.46   429.5 2101.96   449.4 2116.99   459.4 2117.27
   509.4    2148   549.3 2174.61   559.3 2175.09   639.2 2231.63   649.2 2232.25
   739.1 2295.75   749.1 2296.49   759.1 2302.77     789 2326.18     819 2345.96
#Mann= 3 , 0 , 0
       0      .1       0   396.8    .045       0   408.8      .1       0
Bank Sta=396.8,408.8
XS Rating Curve= 0 ,0
Exp/Cntr=0.3,0.1

Type RM Length L Ch R = 1 ,1390.2  ,370.3,360.2,352.1
XS GIS Cut Line= 3
     1920114.663      148215.571     1920018.283      147818.005
     1919882.743      147429.073
#Sta/Elev= 30
       0 2229.11    59.9 2188.97    69.8 2183.61    79.8 2182.69   139.7 2144.09
   169.6 2122.78   179.6 2121.99   209.5  2102.1   229.5 2099.47   379.2 2097.81
   403.1 2092.81   409.1 2092.35   415.1 2093.84   418.9 2094.79   438.5 2113.63
   467.9 2136.15   477.7 2138.77   487.5 2143.41   575.8 2216.31   585.6 2217.44
   595.4 2223.95     664  2281.3   673.9 2287.92   683.7 2289.71   693.5 2296.99
   732.7 2330.25   752.3  2348.3   771.9 2354.87   791.5  2358.7     821 2373.24
#Mann= 3 , 0 , 0
       0      .1       0   403.1    .045       0   415.1      .1       0
Bank Sta=403.1,415.1
XS Rating Curve= 0 ,0
Exp/Cntr=0.3,0.1

Type RM Length L Ch R = 1 ,1030    ,438.2,425,411.8
XS GIS Cut Line= 3
     1920571.864      147956.289     1920475.133      147817.499
     1920047.274      147318.192
#Sta/Elev= 30
       0 2159.81      10 2157.24    39.8 2145.45    89.6 2128.38   109.5 2118.46
   119.4 2114.99   129.4 2113.42   159.2 2102.64   169.2 2100.25   238.9 2090.84
   318.6 2088.22   348.5 2091.28   398.3 2086.05   403.4 2086.17   415.4 2087.01
   428.2 2089.57   438.2 2094.36   468.1 2113.02     488 2129.77     498  2135.4
   507.9  2138.7   607.5 2216.68   627.5 2238.88   637.4 2243.11   657.4 2255.18
   667.3 2258.02   727.1  2265.1     747 2271.87   776.9 2276.16   826.7 2280.12
#Mann= 3 , 0 , 0
       0     .08       0   403.4    .045       0   415.4     .08       0
#XS Ineff= 2 , 0
          348.52 2091.25
Permanent Ineff=
       F       F
Bank Sta=403.4,415.4
XS Rating Curve= 0 ,0
Exp/Cntr=0.3,0.1

Type RM Length L Ch R = 1 ,605     ,422.5,415.5,406.6
XS GIS Cut Line= 3
     1921077.654       147568.18     1920774.085      147399.659
     1920110.988      147235.627
#Sta/Elev= 30
       0 2188.26     9.9 2183.52    19.8 2180.16    69.4 2164.77   178.6 2135.33
   208.3 2130.13   267.8 2113.88   287.7 2106.83   337.3 2092.39   347.2 2090.22
   376.9 2087.82     487 2082.83     499 2082.02   515.5 2081.38   614.5 2084.56
   654.1 2086.58   673.9 2088.52   683.8 2090.88   703.6 2097.15   713.5 2102.91
   733.3  2110.2   782.8 2130.01   792.7 2136.34   802.6 2140.59   842.2 2153.91
     862 2161.56   881.8 2173.51   951.1 2199.32     961 2206.15  1030.3 2228.78
#Mann= 3 , 0 , 0
       0     .08       0     487    .045       0     499     .08       0
Bank Sta=487,499
XS Rating Curve= 0 ,0
Exp/Cntr=0.3,0.1

Type RM Length L Ch R = 1 ,189.6   ,180.1,189.4,200.6
XS GIS Cut Line= 3
     1920909.439      146942.759      1920463.72      146983.219
     1920078.467      147100.084
#Sta/Elev= 30
       0 2081.88   119.4 2081.15     179 2079.85   228.8 2080.38   258.6 2079.11
   397.8 2076.05   427.7 2074.92   428.2 2074.94   440.2 2075.68   447.6 2076.86
     477 2083.15   486.8 2085.49   496.6 2088.46   535.9 2094.74   555.6 2097.04
   565.4 2098.98   575.2 2103.87     585  2107.7   643.9 2126.72   653.8 2130.24
   663.6 2134.69   712.7 2149.29   732.3 2154.69   742.1 2160.87     752 2165.54
   781.4 2175.46   810.9 2189.17   820.7 2194.64   830.5 2201.91   850.1  2210.9
#Mann= 3 , 0 , 0
       0     .08       0   428.2    .045       0   440.2     .08       0
Bank Sta=428.2,440.2
XS Rating Curve= 0 ,0
Exp/Cntr=0.3,0.1

Chan Stop Cuts=-1
Use User Specified Reach Order=0
Composite Channel Slope=5